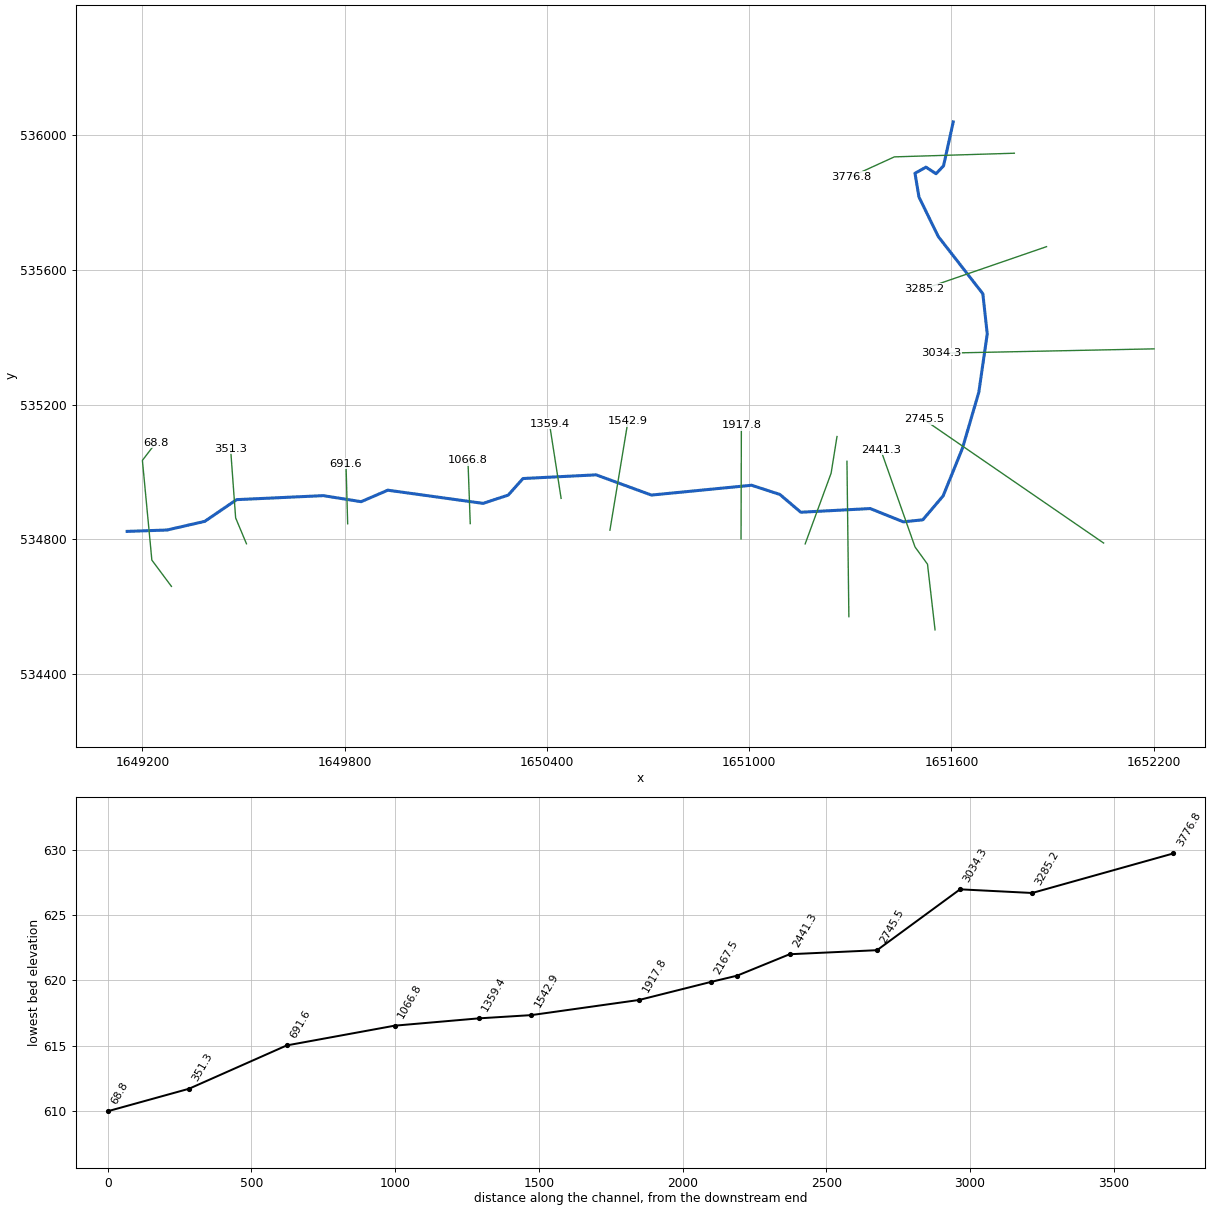
--- RFMillCr.prj (project) ---

Proj Title=RFMillCr
Current Plan=p01
Geom File=g01
Flow File=f01
Plan File=p01
DSS Export Rating Curves=0
DSS Export Rating Curve Sorted=0
DSS Export Volume Flow Curves=0
DXF OffsetX=0
DXF OffsetY=0
DXF ScaleX=0
DXF ScaleY=0

--- RFMillCr.p01 (plan) ---

Plan Title=Floodplain
Program Version=4.00
Geom File=g01
Flow File=f01
K Sum by GR=0
Std Step Tol=0.01
Critical Tol=0.01
Num of Std Step Trials=20
Max Error Tol=0.3
Flow Tol Ratio=0.001
Split Flow NTrial=30
Split Flow Tol=0.02
Split Flow Ratio=0.02
Log Output Level=0
Friction Slope Method=1
Unsteady Friction Slope Method=2
Unsteady Bridges Friction Slope Method=1
Global Log Level=0
CheckData=False
Run HTab=0
Run UNet=0
Run PostProcess=0
UNET Theta=0
UNET Theta Warmup=0
UNET ZTol=0
UNET ZSATol=0
UNET MxIter=0
UNET MaxInSteps=0
UNET DtIC=0
UNET DtMin=0
UNET MaxCRTS=0
UNET WFStab=0
UNET SFStab=0
UNET WFX=0
UNET SFX=0
UNET DSS MLevel=0
UNET DZMax Abort=0
UNET Convert EG Bridges=0
UNET Use Existing IB Tables=0
UNET Froude Limit=0
UNET Froude Power=0
Write IC File=0
Echo Input=False
Echo Output=False
Write Detailed=0

--- RFMillCr.f01 (steady flow) ---

Flow Title=NFF Regression Equation
Program Version=4.10
Number of Profiles= 1
Profile Names=P100yr
River Rch & RM=RFMillCr,Main            ,3776.8
     828
River Rch & RM=RFMillCr,Main            ,2745.5
     988
River Rch & RM=RFMillCr,Main            ,1917.8
    1020
River Rch & RM=RFMillCr,Main            ,1359.4
    1028
River Rch & RM=RFMillCr,Main            ,351.3
    1041
River Rch & RM=RFMillCr,Main            ,68.8
    1042
Boundary for River Rch & Prof#=RFMillCr,Main            , 1
Up Type= 0
Dn Type= 3
Dn Slope=0.00769
DSS Import GetInterval= 0
DSS Import GetPeak= 0
DSS Import FillOption= 0

--- RFMillCr.g01 (geometry) ---

Geom Title=USGS 10m DEM
Program Version=4.10

River Reach=RFMillCr        ,Main
Reach XY= 30
     1651605.458      536040.389      1651576.58      535909.638
     1651554.445        535886.2     1651524.497      535905.732
     1651491.945      535887.503     1651503.664       535817.19
     1651560.883      535699.742     1651693.261      535529.386
     1651706.282      535410.029     1651681.303      535236.634
     1651632.632      535069.548     1651575.473      534928.572
     1651515.116      534857.322     1651457.167      534851.366
      1651359.16      534890.814     1651153.111      534879.871
     1651091.118      534932.732      1651007.24      534960.094
     1650710.031      534930.899     1650545.948      534991.038
     1650328.972      534980.094       1650285.2      534930.867
     1650210.639      534906.227     1649927.837       534945.41
     1649848.825      534911.237     1649736.534      534929.195
     1649479.389      534917.338     1649384.945      534852.755
     1649273.139       534827.06     1649154.612      534822.917

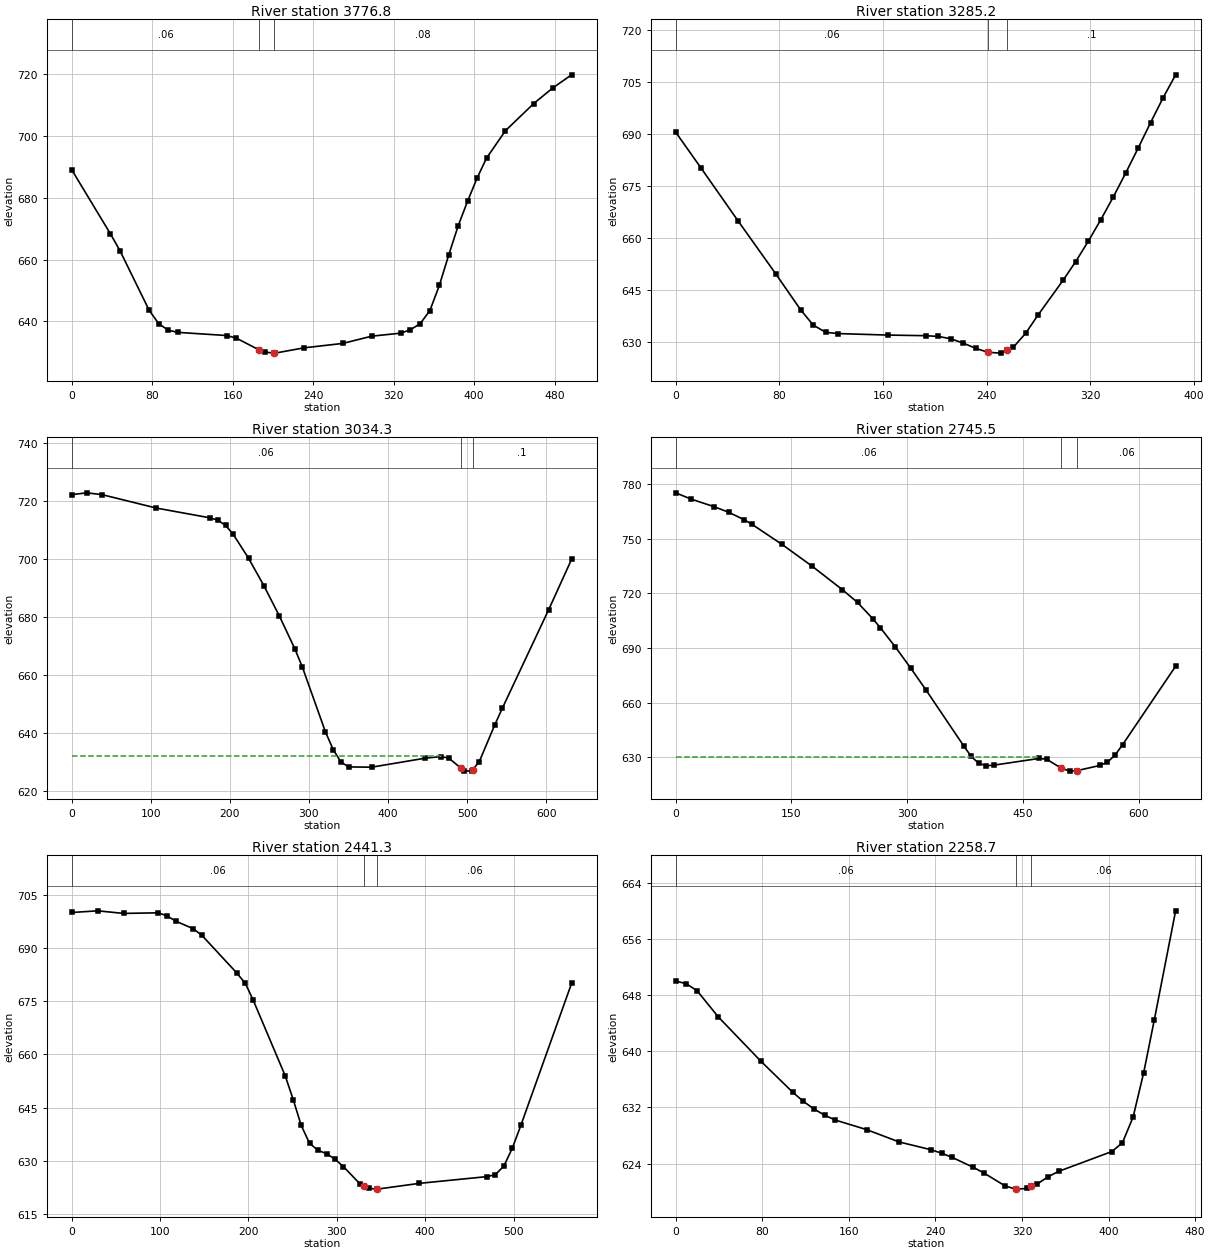
Type RM Length L Ch R = 1 ,3776.8  ,482.4,491.6,498.3
XS GIS Cut Line= 3
     1651786.736      535947.181     1651430.834      535936.331
     1651302.796      535877.737
#Sta/Elev= 30
       0  689.12    38.5  668.37    48.1  662.84      77  643.62    86.6  639.23
    96.2  637.12   105.9  636.44     154  635.43   163.6   634.6   186.4  630.75
   192.5  630.03   201.4  629.75   202.1  629.73     231  631.44   269.5  632.87
   298.3  635.22   327.2   636.2   336.8  637.31   346.4  639.26   356.1  643.51
   365.5  651.67   374.8  661.49   384.2  670.95   393.6  678.96     403  686.41
   412.4  692.86   431.2  701.74   459.3  710.52   478.1  715.54   496.9  719.82
#Mann= 3 , 0 , 0
       0     .06       0   186.4    .045       0   201.4     .08       0
Bank Sta=186.4,201.4
XS Rating Curve= 0 ,0
Exp/Cntr=0.3,0.1

Type RM Length L Ch R = 1 ,3285.2  ,257.2,250.9,244.2
XS GIS Cut Line= 2
     1651882.223      535669.404     1651517.639      535543.536
#Sta/Elev= 30
       0  690.45    19.3  680.24    48.2  664.81    77.1  649.62    96.4  639.18
   106.1   634.8   115.7   632.7   125.4  632.34   163.9  631.91   192.8  631.73
   202.5  631.52   212.1  630.86   221.8   629.6   231.4  628.09   240.9  626.94
   250.7   626.7   255.9  627.59   260.4  628.36     270  632.44   279.6  637.73
   298.9  647.74   308.6  653.12   318.2  658.92   327.8  665.09   337.5  671.69
   347.1  678.62   356.8  685.88   366.4  693.24   376.1  700.44   385.7  707.02
#Mann= 3 , 0 , 0
       0     .06       0   240.9    .045       0   255.9      .1       0
Bank Sta=240.9,255.9
XS Rating Curve= 0 ,0
Exp/Cntr=0.3,0.1

Type RM Length L Ch R = 1 ,3034.3  ,303.2,288.8,274.2
XS GIS Cut Line= 2
     1652201.233      535365.584     1651569.333      535352.608
#Sta/Elev= 30
       0  722.32    19.4  722.94    38.9  722.28     107  717.69     175  714.31
   184.8   713.5   194.5  711.73   204.2  708.66   223.6   700.4   243.1  690.88
   262.5  680.53     282  669.25   291.7  662.84   320.9  640.47   330.6  634.42
   340.3  630.18     350  628.43   379.2  628.34   447.3  631.46   466.7  631.98
   476.5  631.52     492  628.06   495.9  627.11   505.6  626.98     507  627.45
   515.4  630.28   534.8  642.86   544.5  648.67   602.9  682.54     632     700
#Mann= 3 , 0 , 0
       0     .06       0     492    .045       0     507      .1       0
#XS Ineff= 2 , 0
          466.34  632.25
Permanent Ineff=
       F       F
Bank Sta=492,507
XS Rating Curve= 0 ,0
Exp/Cntr=0.3,0.1

Type RM Length L Ch R = 1 ,2745.5  ,316.7,304.2,290.8
XS GIS Cut Line= 2
     1652051.493      534788.327     1651517.998      535155.758
#Sta/Elev= 30
       0  775.35    19.6  771.95    49.1  767.82    68.7  764.65    88.3  760.64
    98.2   758.2   137.4  747.09   176.7  735.03   215.9  722.11   235.6  715.06
   255.2   706.2     265  701.26   284.6   690.6   304.3   679.1   323.9   667.2
     373  636.31   382.8  630.48   392.6  626.61   402.4  625.29   412.2   625.6
   471.1  629.31   480.9  628.79   499.3  624.02   510.4  622.32   520.2  622.61
   549.6  625.43   559.4  627.23   569.3  631.12   579.1  636.86   647.8     680
#Mann= 3 , 0 , 0
       0     .06       0   499.3    .045       0   520.2     .06       0
#XS Ineff= 2 , 0
          471.27  630.15
Permanent Ineff=
       F       F
Bank Sta=499.3,520.2
XS Rating Curve= 0 ,0
Exp/Cntr=0.3,0.1

Type RM Length L Ch R = 1 ,2441.3  ,189.9,182.6,173.2
XS GIS Cut Line= 4
     1651551.441      534530.248     1651529.072      534725.438
     1651492.025      534776.671     1651390.507      535065.197
#Sta/Elev= 30
       0  699.99    29.5  700.46    58.9  699.73    98.2   699.9   108.1     699
   117.9  697.55   137.5  695.42   147.4  693.54   186.6     683   196.5  680.02
   205.5  675.22   241.6  653.97   250.7  647.23   259.7  639.98   269.2  634.91
   278.8  632.94   288.4  632.01   297.9  630.46   307.5  628.35   326.6  623.39
   330.4  622.93   336.2  622.23   345.7  622.01   393.5  623.64     470  625.54
   479.5  626.11   489.1  628.55   498.6  633.56   508.2  639.96   565.6  679.99
#Mann= 3 , 0 , 0
       0     .06       0   330.4    .045       0   345.7     .06       0
Bank Sta=330.4,345.7
XS Rating Curve= 0 ,0
Exp/Cntr=0.3,0.1

Type RM Length L Ch R = 1 ,2258.7  ,99.7,91.2,81
XS GIS Cut Line= 2
      1651295.78      534569.374     1651290.103      535031.323
#Sta/Elev= 30
       0  650.01     9.8  649.61    19.7  648.63    39.3   644.9    78.6   638.6
   108.1  634.17     118  632.86   127.8  631.78   137.6   630.9   147.4  630.21
   176.9  628.82   206.4  627.09   235.9  625.98   245.7  625.49   255.6  624.88
   275.2  623.46     285  622.65   304.7   620.8   314.5  620.37   324.4  620.46
   328.8  620.75   334.2  621.11     344  622.12   353.9   622.9     403  625.72
   412.8  626.96   422.7  630.63   432.5  636.96   442.3  644.47     462     660
#Mann= 3 , 0 , 0
       0     .06       0   314.5    .045       0   328.8     .06       0
Bank Sta=314.5,328.8
XS Rating Curve= 0 ,0
Exp/Cntr=0.3,0.1

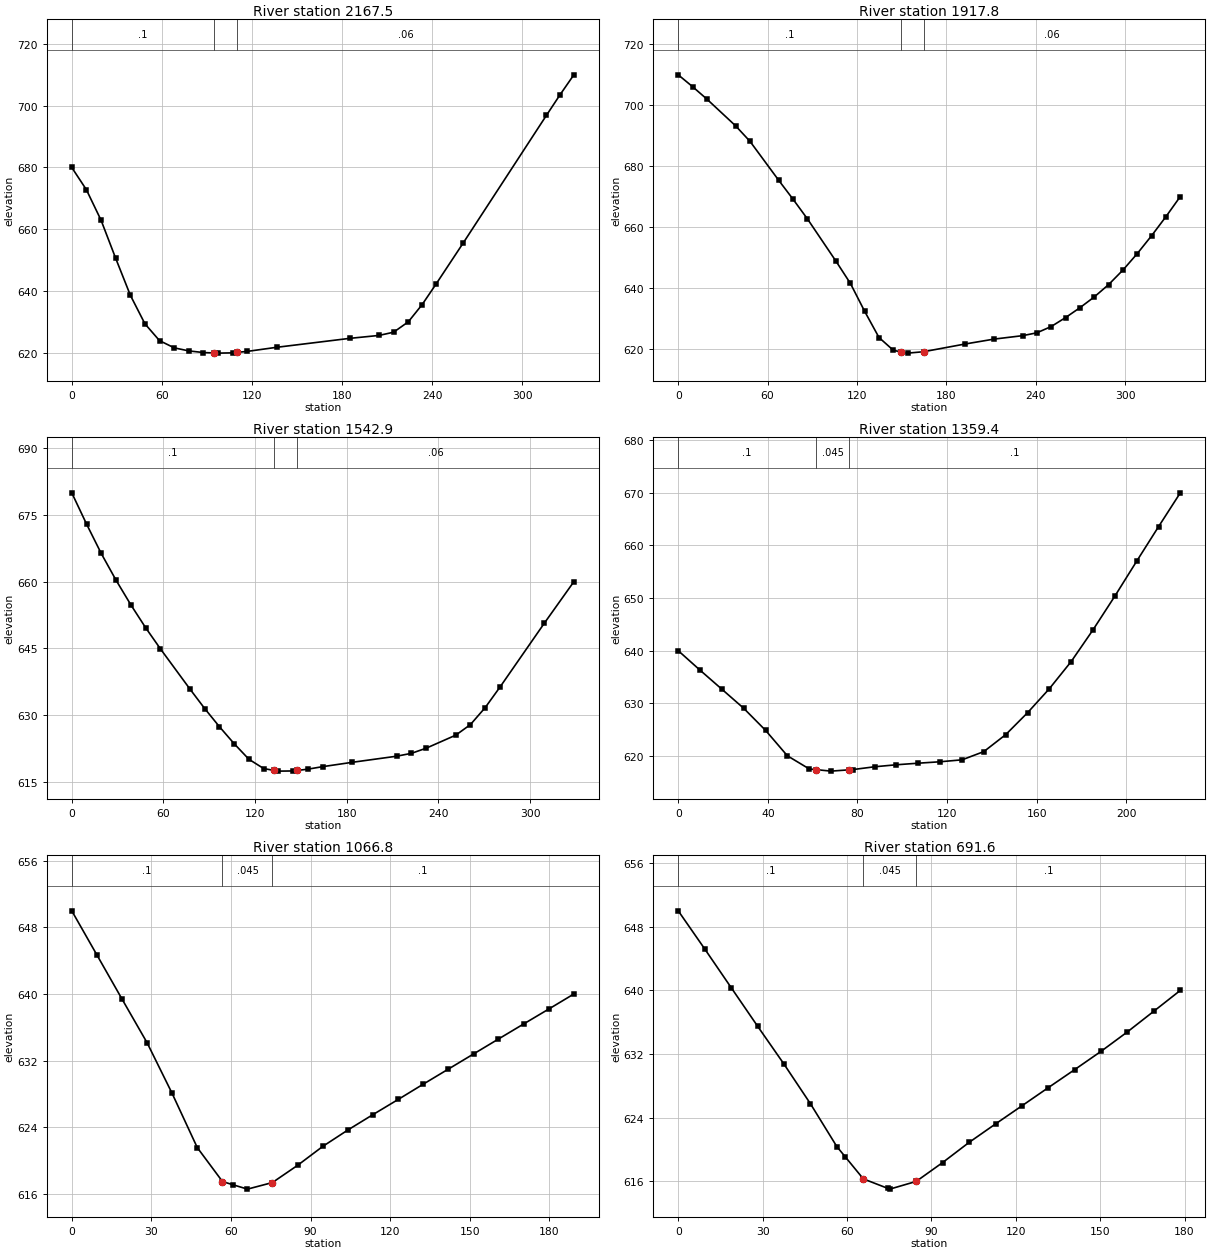
Type RM Length L Ch R = 1 ,2167.5  ,241.6,249.7,259.3
XS GIS Cut Line= 3
     1651166.136      534785.729     1651243.141      534996.028
     1651260.575      535104.937
#Sta/Elev= 26
       0     680     9.7  672.83    19.5  662.92    29.2  650.63      39  638.62
    48.7  629.38    58.4  623.94    68.2   621.6    77.9  620.61    87.6  620.08
    94.9  619.94    97.4  619.89   107.1  619.98   109.9  620.12   116.8  620.45
   136.3  621.77     185  624.67   204.5  625.62   214.2  626.66     224  630.02
   233.2  635.59   242.3  642.12   260.7  655.66   315.9  696.84   325.1  703.61
   334.2     710
#Mann= 3 , 0 , 0
       0      .1       0    94.9    .045       0   109.9     .06       0
Bank Sta=94.9,109.9
XS Rating Curve= 0 ,0
Exp/Cntr=0.3,0.1

Type RM Length L Ch R = 1 ,1917.8  ,378.7,374.8,370.7
XS GIS Cut Line= 2
     1650975.876      534800.696     1650976.878      535137.808
#Sta/Elev= 30
       0     710     9.6  706.12    19.3  701.99    38.5  693.24    48.2  688.12
    67.4  675.36      77  669.16    86.7  662.67     106  648.67   115.6  641.42
   125.2  632.22   134.8  623.64   144.5  619.41   149.7  618.92   154.1  618.51
   164.7  618.97   192.6  621.51   211.9  623.11   231.2  624.25   240.8  625.19
   250.4  627.25   260.1  630.21   269.7  633.44   279.3  636.97     289  641.06
   298.6  645.83   308.2  651.23   317.8   657.1   327.5  663.41   337.1     670
#Mann= 3 , 0 , 0
       0      .1       0   149.7    .045       0   164.7     .06       0
Bank Sta=149.7,164.7
XS Rating Curve= 0 ,0
Exp/Cntr=0.3,0.1

Type RM Length L Ch R = 1 ,1542.9  ,176.1,183.5,190.7
XS GIS Cut Line= 2
     1650586.947      534826.617     1650640.498      535150.909
#Sta/Elev= 29
       0  680.01     9.7  672.96    19.3  666.35      29  660.33    38.7  654.78
    48.3  649.67      58   644.9    77.3  635.86      87  631.45    96.7  627.34
   106.3  623.53     116  620.01   125.7  617.92   132.7   617.5   135.3  617.35
     145  617.39   147.7   617.5   154.7   617.8   164.3  618.36   183.7  619.34
   212.7  620.71   222.4  621.36     232  622.51   251.4  625.45     261  627.83
   270.7  631.67   280.4   636.3   309.4  650.67   328.7     660
#Mann= 3 , 0 , 0
       0      .1       0   132.7    .045       0   147.7     .06       0
Bank Sta=132.7,147.7
XS Rating Curve= 0 ,0
Exp/Cntr=0.3,0.1

Type RM Length L Ch R = 1 ,1359.4  ,293.7,292.7,289.8
XS GIS Cut Line= 2
      1650442.09      534921.096     1650407.655      535142.539
#Sta/Elev= 26
       0  639.99     9.7   636.3    19.5  632.66    29.2  629.05      39  624.84
    48.7  620.02    58.5  617.51    61.4  617.39    68.2   617.1    76.4  617.35
      78   617.4    87.7  617.93    97.4  618.31   107.2  618.61   116.9  618.88
   126.7  619.25   136.4  620.81   146.2  624.05   155.9  628.19   165.6  632.74
   175.4  637.93   185.1  643.93   194.9  650.37   204.6  656.98   214.4  663.57
   224.1  669.99
#Mann= 3 , 0 , 0
       0      .1       0    61.4    .045       0    76.4      .1       0
Bank Sta=61.4,76.4
XS Rating Curve= 0 ,0
Exp/Cntr=0.3,0.1

Type RM Length L Ch R = 1 ,1066.8  ,376.2,375.2,375
XS GIS Cut Line= 2
     1650172.526      534846.173     1650165.668      535035.259
#Sta/Elev= 22
       0     650     9.5  644.68    18.9  639.41    28.4  634.13    37.8  628.06
    47.3  621.53    56.8  617.45    60.6  617.08    66.2  616.54    75.6  617.33
    85.1   619.4    94.6  621.68   104.1  623.66   113.5   625.5     123  627.32
   132.4  629.15   141.9  630.97   151.4  632.79   160.8  634.59   170.3   636.4
   179.8   638.2   189.2     640
#Mann= 3 , 0 , 0
       0      .1       0    56.8    .045       0    75.6      .1       0
Bank Sta=56.8,75.6
XS Rating Curve= 0 ,0
Exp/Cntr=0.3,0.1

Type RM Length L Ch R = 1 ,691.6   ,341.3,340.3,340.2
XS GIS Cut Line= 2
     1649808.835      534845.691     1649803.885      535024.157
#Sta/Elev= 22
       0     650     9.4  645.22    18.8  640.36    28.2  635.51    37.6  630.74
      47  625.76    56.4  620.37    59.4  619.08    65.8  616.32    74.4  615.14
    75.2  615.03    84.6     616      94  618.37   103.4   620.9   112.8  623.22
   122.2   625.5   131.6  627.79     141  630.06   150.3  632.34   159.7  634.79
   169.1  637.39   178.5     640
#Mann= 3 , 0 , 0
       0      .1       0    65.8    .045       0    84.6      .1       0
Bank Sta=65.8,84.6
XS Rating Curve= 0 ,0
Exp/Cntr=0.3,0.1

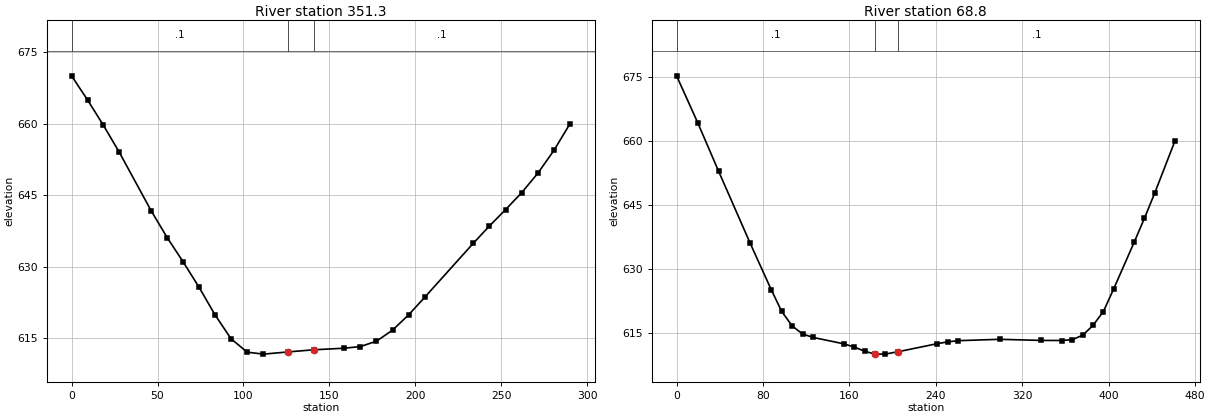
Type RM Length L Ch R = 1 ,351.3   ,279,282.5,284.4
XS GIS Cut Line= 3
      1649508.61      534786.099     1649476.498      534863.068
     1649461.459      535069.237
#Sta/Elev= 27
       0     670     9.3  664.94    18.5  659.65    27.8  653.96    46.3  641.74
    55.6  636.13    64.9  631.04    74.1  625.76    83.4  619.97    92.8  614.92
   102.2  612.12   111.6  611.71     126  612.17     141  612.62   158.6  612.95
     168  613.29   177.4  614.42   186.8  616.74   196.2  619.97   205.6  623.66
   233.7  634.91   243.1  638.53   252.5  641.97   261.9  645.52   271.3  649.59
   280.7   654.4   290.1     660
#Mann= 3 , 0 , 0
       0      .1       0     126    .045       0     141      .1       0
Bank Sta=126,141
XS Rating Curve= 0 ,0
Exp/Cntr=0.3,0.1

Type RM Length L Ch R = 1 ,68.8    ,73.1,68.8,63.2
XS GIS Cut Line= 4
     1649286.013      534659.451     1649227.962      534737.589
     1649199.897      535034.052     1649240.128      535086.861
#Sta/Elev= 30
       0  675.16    19.5  664.22    38.9  652.82    68.1  635.97    87.6  625.09
    97.3     620     107  616.59   116.6  614.71   126.2  613.91     155  612.39
   164.6  611.63   174.2  610.66   183.8  609.99   193.4  610.01   204.6  610.53
   241.4  612.44     251  612.85   260.6  613.14   299.1  613.46   337.5   613.2
   356.7  613.18   366.3  613.38   375.9  614.41   385.5  616.72   395.1  619.96
   404.6  625.25   423.6  636.19   433.1   641.8   442.6  647.69   461.5     660
#Mann= 3 , 0 , 0
       0      .1       0   183.8    .045       0   204.6      .1       0
Bank Sta=183.8,204.6
XS Rating Curve= 0 ,0
Exp/Cntr=0.3,0.1

Chan Stop Cuts=-1
Use User Specified Reach Order=0
Composite Channel Slope=5